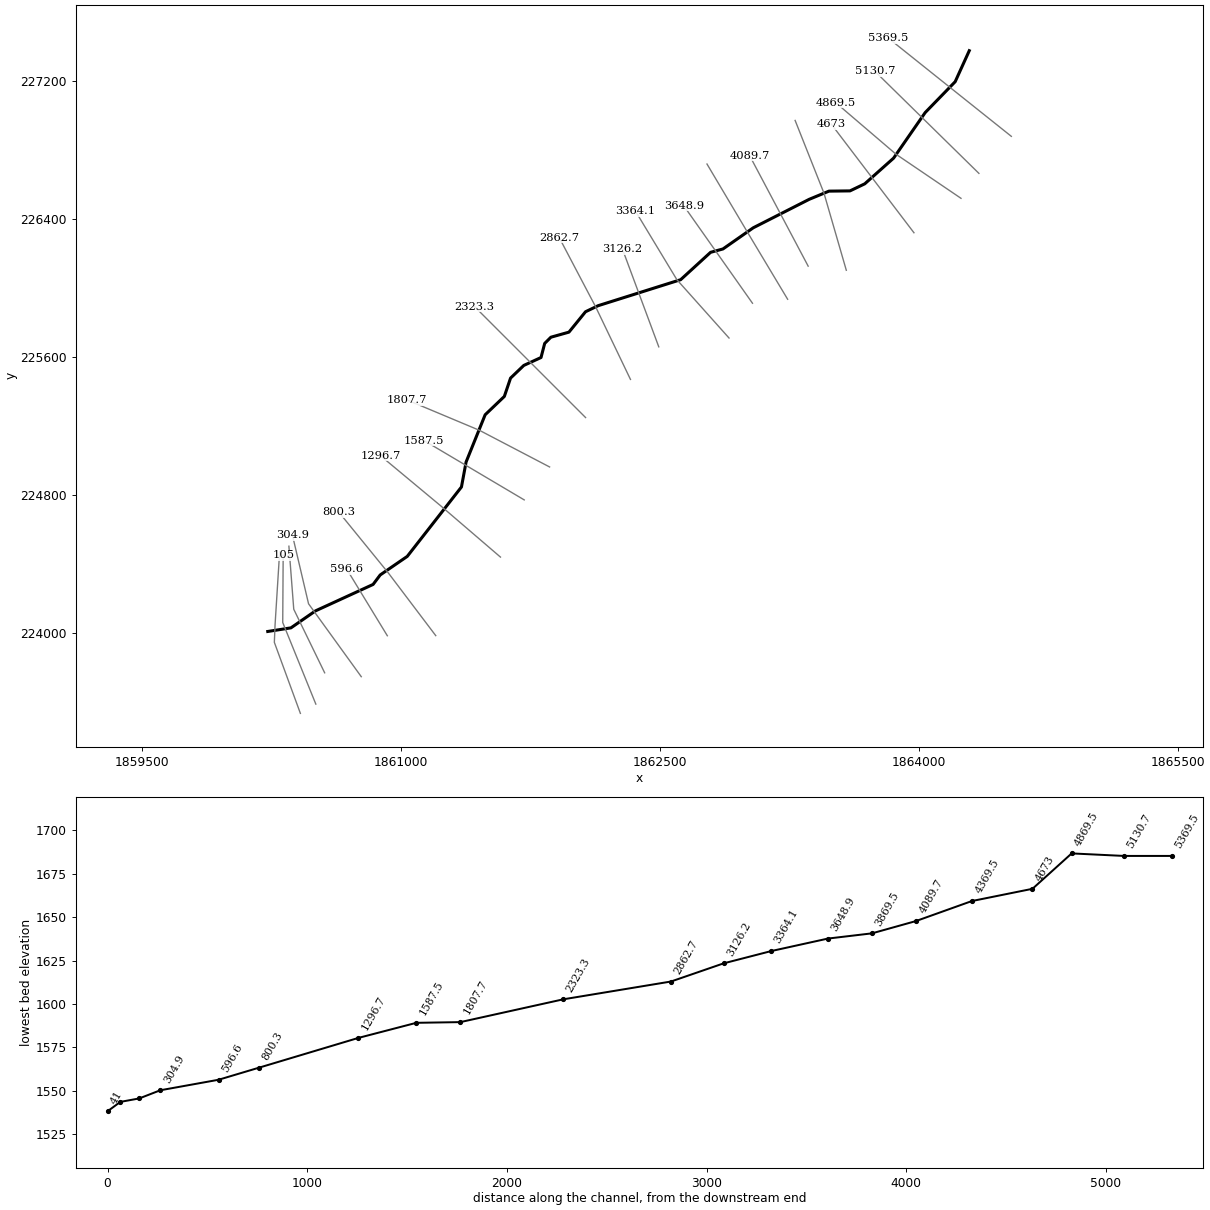
--- RtFkCedrCr.prj (project) ---

Proj Title=RtFkCedrCr
Current Plan=p01
Geom File=g01
Flow File=f01
Plan File=p01
DSS Export Rating Curves=0
DSS Export Rating Curve Sorted=0
DSS Export Volume Flow Curves=0
DXF OffsetX=0
DXF OffsetY=0
DXF ScaleX=0
DXF ScaleY=0

--- RtFkCedrCr.p01 (plan) ---

Plan Title=Floodplain
Program Version=4.00
Geom File=g01
Flow File=f01
K Sum by GR=0
Std Step Tol=0.01
Critical Tol=0.01
Num of Std Step Trials=20
Max Error Tol=0.3
Flow Tol Ratio=0.001
Split Flow NTrial=30
Split Flow Tol=0.02
Split Flow Ratio=0.02
Log Output Level=0
Friction Slope Method=1
Unsteady Friction Slope Method=2
Unsteady Bridges Friction Slope Method=1
Global Log Level=0
CheckData=False
Run HTab=0
Run UNet=0
Run PostProcess=0
UNET Theta=0
UNET Theta Warmup=0
UNET ZTol=0
UNET ZSATol=0
UNET MxIter=0
UNET MaxInSteps=0
UNET DtIC=0
UNET DtMin=0
UNET MaxCRTS=0
UNET WFStab=0
UNET SFStab=0
UNET WFX=0
UNET SFX=0
UNET DSS MLevel=0
UNET DZMax Abort=0
UNET Convert EG Bridges=0
UNET Use Existing IB Tables=0
UNET Froude Limit=0
UNET Froude Power=0
Write IC File=0
Echo Input=False
Echo Output=False
Write Detailed=0

--- RtFkCedrCr.f01 (steady flow) ---

Flow Title=NFF Regression Equation
Program Version=4.00
Number of Profiles=1
Profile Names=P100yr
River Rch & RM=RtFkCedrCr,Main      ,5369.5
583.0497
River Rch & RM=RtFkCedrCr,Main      ,3869.5
633.4086
River Rch & RM=RtFkCedrCr,Main      ,2862.7
658.0440
River Rch & RM=RtFkCedrCr,Main      ,1296.7
700.8891
River Rch & RM=RtFkCedrCr,Main      ,199.6
764.4470
Boundary for River Rch & Prof#=RtFkCedrCr,Main      ,1
Up Type=0
Dn Type=3
Dn Slope=0.050194

--- RtFkCedrCr.g01 (geometry) ---

Geom Title=USGS 10m DEM
Program Version=4.00

River Reach=RtFkCedrCr     ,Main
Reach XY= 30
     1864290.370      227375.598     1864208.655      227195.824
     1864034.949      227017.050     1863851.831      226752.835
     1863684.758      226604.001     1863599.398      226563.145
     1863477.559      226561.686     1863363.015      226514.264
     1863039.084      226349.379     1862863.615      226226.677
     1862791.705      226207.065     1862618.468      226048.536
     1862140.246      225897.772     1862067.289      225862.752
     1861971.281      225744.554     1861866.685      225715.137
     1861830.730      225679.182     1861809.484      225597.466
     1861709.791      225551.706     1861632.978      225478.161
     1861597.023      225371.931     1861485.890      225265.701
     1861375.438      224991.860     1861348.608      224847.317
     1861034.460      224444.872     1860877.925      224337.411
     1860836.698      224282.441     1860503.078      224129.280
     1860360.811      224030.788     1860226.480      224009.849

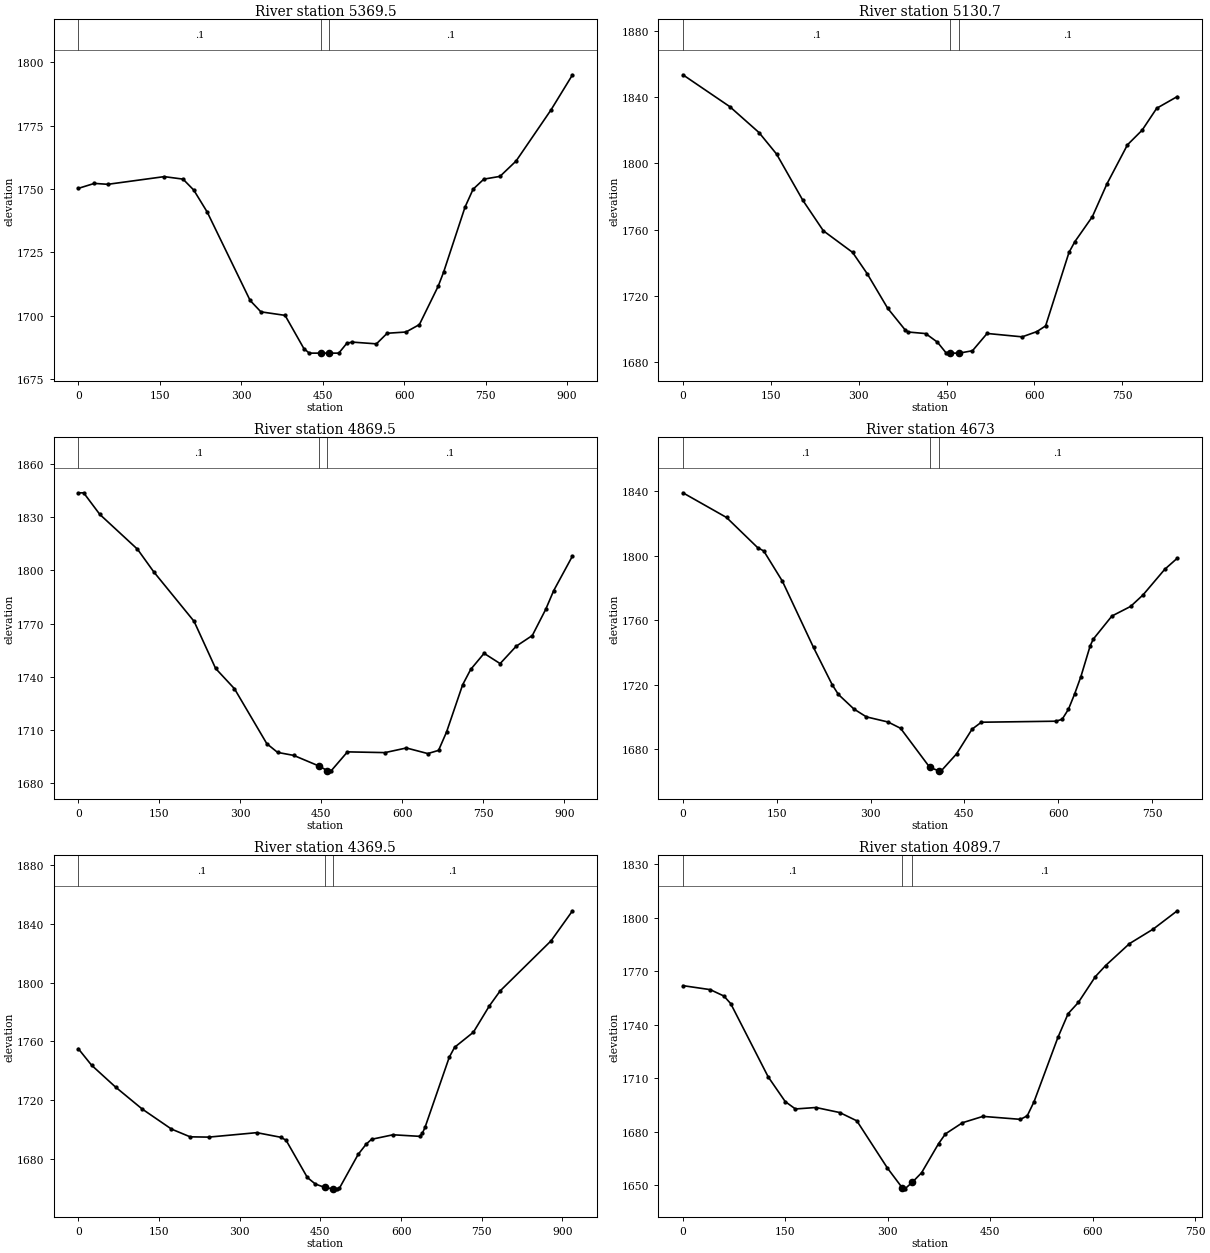
Type RM Length L Ch R = 1 ,5369.5,241,238.7,236.4
XS GIS Cut Line= 3
     1864534.007      226879.189     1864178.412      227163.050
     1863823.045      227447.198
#Sta/Elev= 30
       0 1750.21    29.7 1752.18    54.4 1751.82   158.3 1754.85   192.9 1753.87
   212.7 1749.54   237.4 1740.89   316.5 1705.98   336.3 1701.50   380.8 1700.11
   415.4 1687.02   425.3 1685.21   447.5 1685.21   462.5 1685.21   479.7 1685.21
   494.6 1689.12   504.5 1689.56   549.0 1688.87   568.8 1693.05   603.4 1693.54
   628.1 1696.47   662.7 1711.60   672.6 1717.10   712.2 1742.86   727.0 1749.89
   746.8 1753.86   776.5 1754.95   806.1 1761.00   870.4 1781.16   910.0 1795.02
#Mann= 3 , 0 , 0
       0     0.1       0   447.5   0.045       0   462.5     0.1       0
Bank Sta=   447.5,   462.5
Exp/Cntr=0.3,0.1

Type RM Length L Ch R = 1 ,5130.7,257.2,261.3,262.9
XS GIS Cut Line= 2
     1864346.167      226664.574     1863744.111      227255.879
#Sta/Elev= 30
       0 1853.62    79.9 1834.38   129.8 1818.70   159.8 1805.68   204.7 1777.67
   239.7 1759.24   289.6 1746.18   314.6 1733.25   349.5 1712.38   379.5 1699.20
   384.5 1697.99   414.4 1697.04   434.4 1691.87   449.4 1685.31   454.4 1685.21
   456.7 1685.21   471.7 1685.21   494.3 1686.65   519.3 1697.11   579.2 1695.06
   604.2 1698.23   619.2 1701.69   659.1 1746.13   669.1 1752.64   699.1 1767.83
   724.0 1787.68   759.0 1811.29   784.0 1820.12   808.9 1833.38   843.9 1840.44
#Mann= 3 , 0 , 0
       0     0.1       0   456.7   0.045       0   471.7     0.1       0
Bank Sta=   456.7,   471.7
Exp/Cntr=0.3,0.1

Type RM Length L Ch R = 1 ,4869.5,203.8,196.4,191.6
XS GIS Cut Line= 3
     1864242.416      226520.072     1863866.827      226774.934
     1863516.336      227074.787
#Sta/Elev= 30
       0 1843.80    10.0 1843.84    39.9 1831.66   109.7 1811.99   139.7 1799.25
   214.5 1771.25   254.4 1744.64   289.3 1733.18   349.2 1702.14   369.1 1697.24
   399.0 1695.54   446.4 1689.46   461.4 1686.88   463.8 1686.66   468.8 1687.01
   498.5 1697.54   568.0 1697.12   607.6 1699.74   647.3 1696.57   667.2 1698.38
   682.0 1708.76   711.8 1735.44   726.7 1744.10   751.5 1753.18   781.2 1747.39
   811.0 1757.22   840.8 1763.25   865.6 1778.02   880.4 1788.60   915.2 1808.16
#Mann= 3 , 0 , 0
       0     0.1       0   446.4   0.045       0   461.4     0.1       0
Bank Sta=   446.4,   461.4
Exp/Cntr=0.3,0.1

Type RM Length L Ch R = 1 ,4673,311.8,303.6,297.5
XS GIS Cut Line= 2
     1863969.882      226320.543     1863491.463      226949.476
#Sta/Elev= 30
       0 1839.05    69.6 1823.76   119.3 1805.06   129.2 1802.94   159.0 1784.16
   208.7 1743.07   238.6 1719.93   248.5 1713.89   273.4 1704.82   293.2 1699.98
   328.0 1696.77   347.9 1692.88   394.4 1668.71   409.4 1666.37   412.5 1666.29
   437.4 1676.99   462.2 1692.34   477.1 1696.65   596.4 1697.28   606.3 1698.50
   616.3 1704.69   626.2 1714.19   636.2 1724.94   651.1 1744.13   656.0 1748.22
   685.8 1762.57   715.7 1768.53   735.6 1775.69   770.3 1791.58   790.2 1798.42
#Mann= 3 , 0 , 0
       0     0.1       0   394.4   0.045       0   409.4     0.1       0
Bank Sta=   394.4,   409.4
Exp/Cntr=0.3,0.1

Type RM Length L Ch R = 1 ,4369.5,275.1,279.7,282.2
XS GIS Cut Line= 3
     1863578.005      226103.084     1863448.569      226550.190
     1863281.523      226971.430
#Sta/Elev= 30
       0 1755.02    24.8 1743.71    69.3 1728.83   118.8 1713.86   173.3 1700.17
   208.0 1694.89   242.6 1694.70   331.8 1697.74   376.3 1694.60   386.2 1692.61
   425.8 1667.18   440.7 1662.71     458 1660.42     473 1659.42   480.4 1659.24
   485.4 1659.86   520.2 1682.90   535.2 1689.93   545.1 1693.20   585.0 1696.29
   634.8 1695.22   639.8 1697.48   644.7 1701.54   689.6 1749.18   699.5 1755.95
   734.4 1766.20   764.2 1784.21   784.2 1794.40   878.8 1828.53   918.6 1848.97
#Mann= 3 , 0 , 0
       0     0.1       0     458   0.045       0     473     0.1       0
Bank Sta=     458,     473
Exp/Cntr=0.3,0.1

Type RM Length L Ch R = 1 ,4089.7,219.1,220.3,221.4
XS GIS Cut Line= 2
     1863357.075      226127.025     1863018.419      226766.709
#Sta/Elev= 30
       0 1761.81    39.9 1759.58    59.9 1756.00    69.9 1751.75   124.8 1710.67
   149.8 1696.80   164.7 1692.68   194.7 1693.50   229.6 1690.67   254.6 1686.03
   299.5 1659.51   320.8 1648.65   324.5 1647.74   335.8 1651.56   349.4 1656.90
   374.4 1673.28   384.4 1678.71   409.3 1684.96   439.3 1688.52   494.2 1686.86
   504.2 1688.85   514.2 1696.79   549.1 1732.79   564.1 1746.14   579.0 1752.38
   604.0 1766.90   619.0 1773.10   653.9 1785.37   688.9 1793.58   723.8 1803.76
#Mann= 3 , 0 , 0
       0     0.1       0   320.8   0.045       0   335.8     0.1       0
Bank Sta=   320.8,   335.8
Exp/Cntr=0.3,0.1

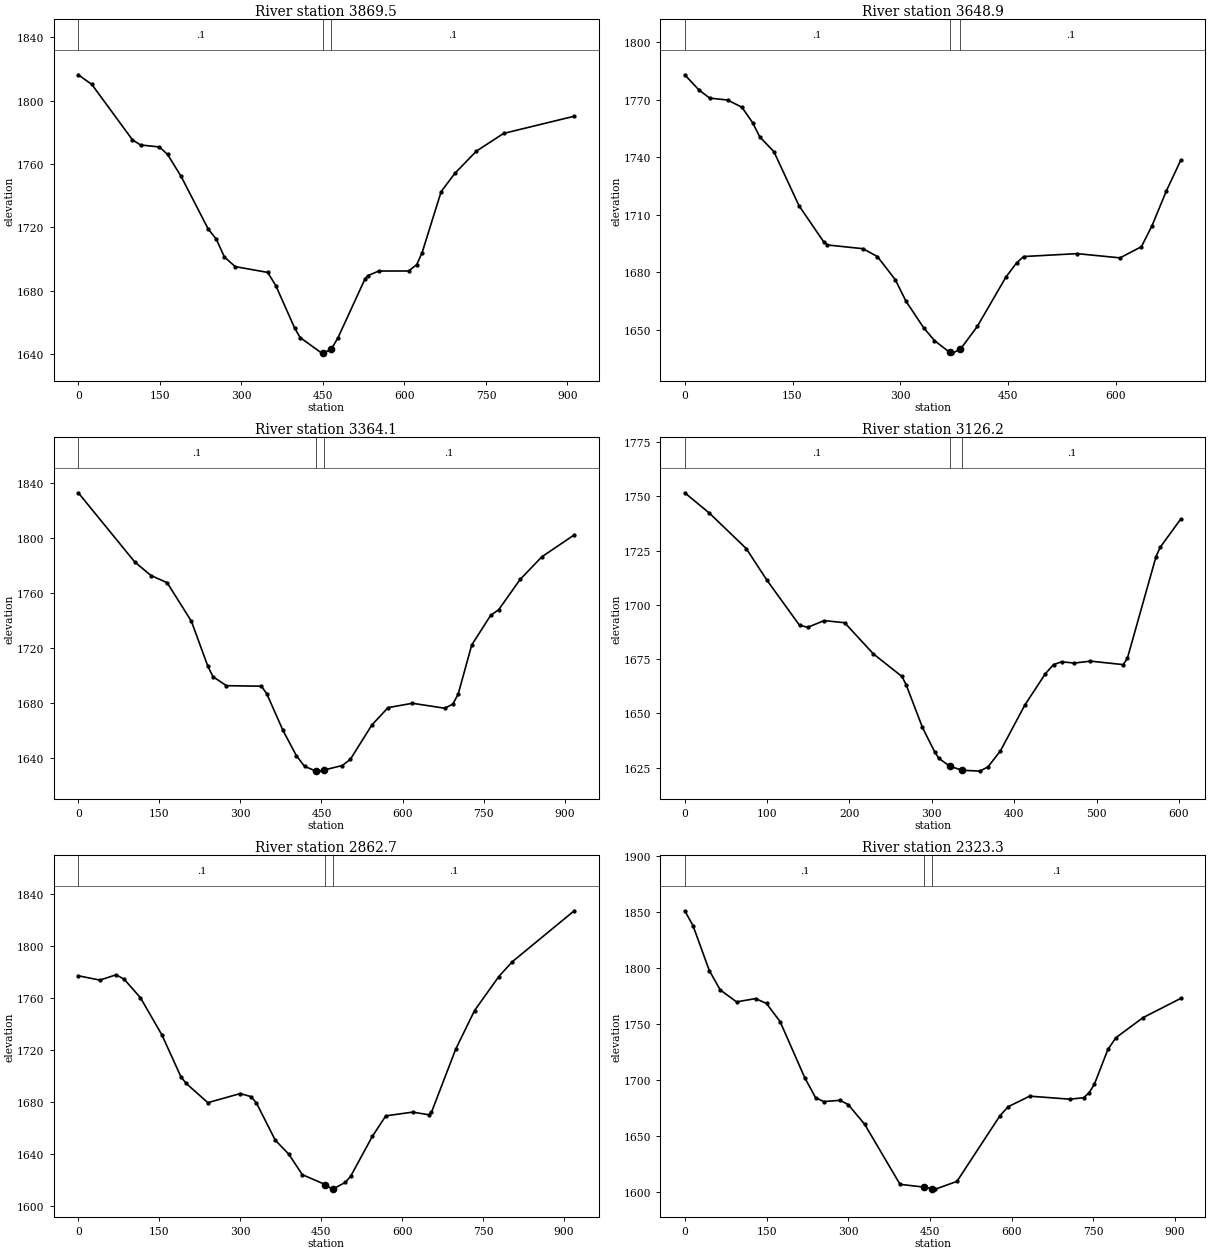
Type RM Length L Ch R = 1 ,3869.5,219.5,220.6,221.8
XS GIS Cut Line= 3
     1863238.120      225935.113     1863002.910      226327.914
     1862770.969      226718.775
#Sta/Elev= 30
       0 1816.37    24.9 1810.28    99.5 1775.36   114.5 1772.08   149.3 1770.82
   164.2 1766.09   189.1 1752.23   238.9 1719.05   253.8 1712.66   268.7 1701.39
   288.6 1695.29   348.4 1691.62   363.3 1683.32   398.1 1656.43   408.1 1650.50
   447.9 1640.66   450.3 1640.68   465.3 1643.07   477.8 1650.41   527.8 1687.76
   532.8 1689.58   552.7 1692.49   607.7 1692.52   622.7 1696.56   632.6 1704.17
   667.6 1742.65   692.6 1754.08   732.5 1768.21   782.5 1779.38   912.3 1790.22
#Mann= 3 , 0 , 0
       0     0.1       0   450.3   0.045       0   465.3     0.1       0
Bank Sta=   450.3,   465.3
Exp/Cntr=0.3,0.1

Type RM Length L Ch R = 1 ,3648.9,281.5,284.7,284.2
XS GIS Cut Line= 2
     1863034.545      225912.005     1862636.758      226476.432
#Sta/Elev= 30
       0 1783.03    19.9 1775.05    34.8 1770.86    59.6 1769.87    79.5 1766.12
    94.4 1758.08   104.3 1750.69   124.2 1742.82   159.0 1714.68   193.7 1695.67
   198.7 1694.15   248.4 1692.20   268.3 1688.06   293.1 1676.04   308.0 1664.79
   332.8 1650.81   347.7 1644.22   368.8 1638.09   372.6 1637.66   383.8 1639.69
   407.4 1651.64   447.1 1677.32   462.0 1684.77   471.9 1688.11   546.4 1689.63
   606.1 1687.42   635.9 1693.26   650.8 1704.32   670.6 1722.35   690.5 1738.30
#Mann= 3 , 0 , 0
       0     0.1       0   368.8   0.045       0   383.8     0.1       0
Bank Sta=   368.8,   383.8
Exp/Cntr=0.3,0.1

Type RM Length L Ch R = 1 ,3364.1,247.1,237.9,232.5
XS GIS Cut Line= 3
     1862898.613      225710.483     1862596.493      226048.607
     1862356.582      226446.004
#Sta/Elev= 30
       0 1832.89   104.6 1782.51   134.5 1772.73   164.4 1767.52   209.3 1739.42
   239.2 1707.25   249.1 1699.17   274.0 1692.61   338.8 1692.22   348.8 1686.68
   378.7 1660.07   403.6 1641.65   418.6 1633.94   439.8 1630.47   443.5 1630.45
   454.8 1631.28   488.4 1634.51   503.4 1639.02   543.3 1664.06   573.2 1676.64
   618.2 1679.81   678.0 1676.21   693.0 1679.17   703.0 1686.55   728.0 1722.18
   762.9 1743.68   777.9 1747.87   817.8 1769.98   857.7 1786.31   917.6 1802.26
#Mann= 3 , 0 , 0
       0     0.1       0   439.8   0.045       0   454.8     0.1       0
Bank Sta=   439.8,   454.8
Exp/Cntr=0.3,0.1

Type RM Length L Ch R = 1 ,3126.2,261.5,263.6,266.5
XS GIS Cut Line= 2
     1862491.620      225659.356     1862281.975      226223.784
#Sta/Elev= 30
       0 1751.58    29.9 1742.22    74.6 1725.92    99.5 1711.46   139.3 1690.58
   149.3 1689.64   169.2 1692.72   194.1 1691.75   228.9 1677.42   263.7 1666.98
   268.7 1663.26   288.6 1643.49   303.5 1632.21   308.5 1629.29   321.8 1625.64
   336.8 1623.80   358.3 1623.39   368.2 1625.35   383.2 1632.68   413.0 1653.86
   437.9 1668.30   447.8 1672.46   457.8 1673.77   472.7 1673.15   492.6 1674.05
   532.4 1672.45   537.4 1675.30   572.2 1722.17   577.2 1726.44   602.1 1739.43
#Mann= 3 , 0 , 0
       0     0.1       0   321.8   0.045       0   336.8     0.1       0
Bank Sta=   321.8,   336.8
Exp/Cntr=0.3,0.1

Type RM Length L Ch R = 1 ,2862.7,536.5,539.4,548.3
XS GIS Cut Line= 3
     1862327.643      225470.588     1862126.677      225889.764
     1861915.559      226291.373
#Sta/Elev= 30
       0 1776.96    40.0 1773.65    70.0 1777.73    85.0 1774.29   115.0 1760.15
   155.0 1731.37   189.9 1699.44   199.9 1694.16   239.9 1679.42   299.9 1686.40
   319.9 1684.08   329.9 1679.23   364.9 1650.55   389.9 1639.81   414.9 1624.08
   457.4 1616.46   469.8 1612.94   472.4 1613.16   494.8 1618.16   504.8 1623.02
   544.6 1653.42   569.6 1669.28   619.4 1672.14   649.3 1670.13   654.3 1672.08
   699.2 1720.57   734.1 1750.27   779.0 1776.37   803.9 1787.74   918.6 1826.91
#Mann= 3 , 0 , 0
       0     0.1       0   457.4   0.045       0   472.4     0.1       0
Bank Sta=   457.4,   472.4
Exp/Cntr=0.3,0.1

Type RM Length L Ch R = 1 ,2323.3,509.7,515.6,523.4
XS GIS Cut Line= 3
     1862067.647      225249.556     1861745.914      225571.290
     1861424.181      225893.024
#Sta/Elev= 30
       0 1851.15    15.0 1838.03    45.0 1797.82    65.0 1780.51    95.0 1769.88
   130.0 1772.80   150.0 1768.44   175.0 1752.16   220.0 1702.31   240.0 1684.33
   255.0 1680.86   285.0 1681.99   300.0 1678.13   330.0 1660.68   395.0 1606.98
   439.3 1604.49   454.3 1602.93   460.0 1602.70   499.5 1609.61   578.6 1668.36
   593.5 1676.28   633.0 1685.70   707.2 1682.97   732.0 1684.33   741.8 1688.55
   751.7 1696.32   776.5 1727.36   791.3 1737.91   840.8 1755.74   910.0 1772.92
#Mann= 3 , 0 , 0
       0     0.1       0   439.3   0.045       0   454.3     0.1       0
Bank Sta=   439.3,   454.3
Exp/Cntr=0.3,0.1

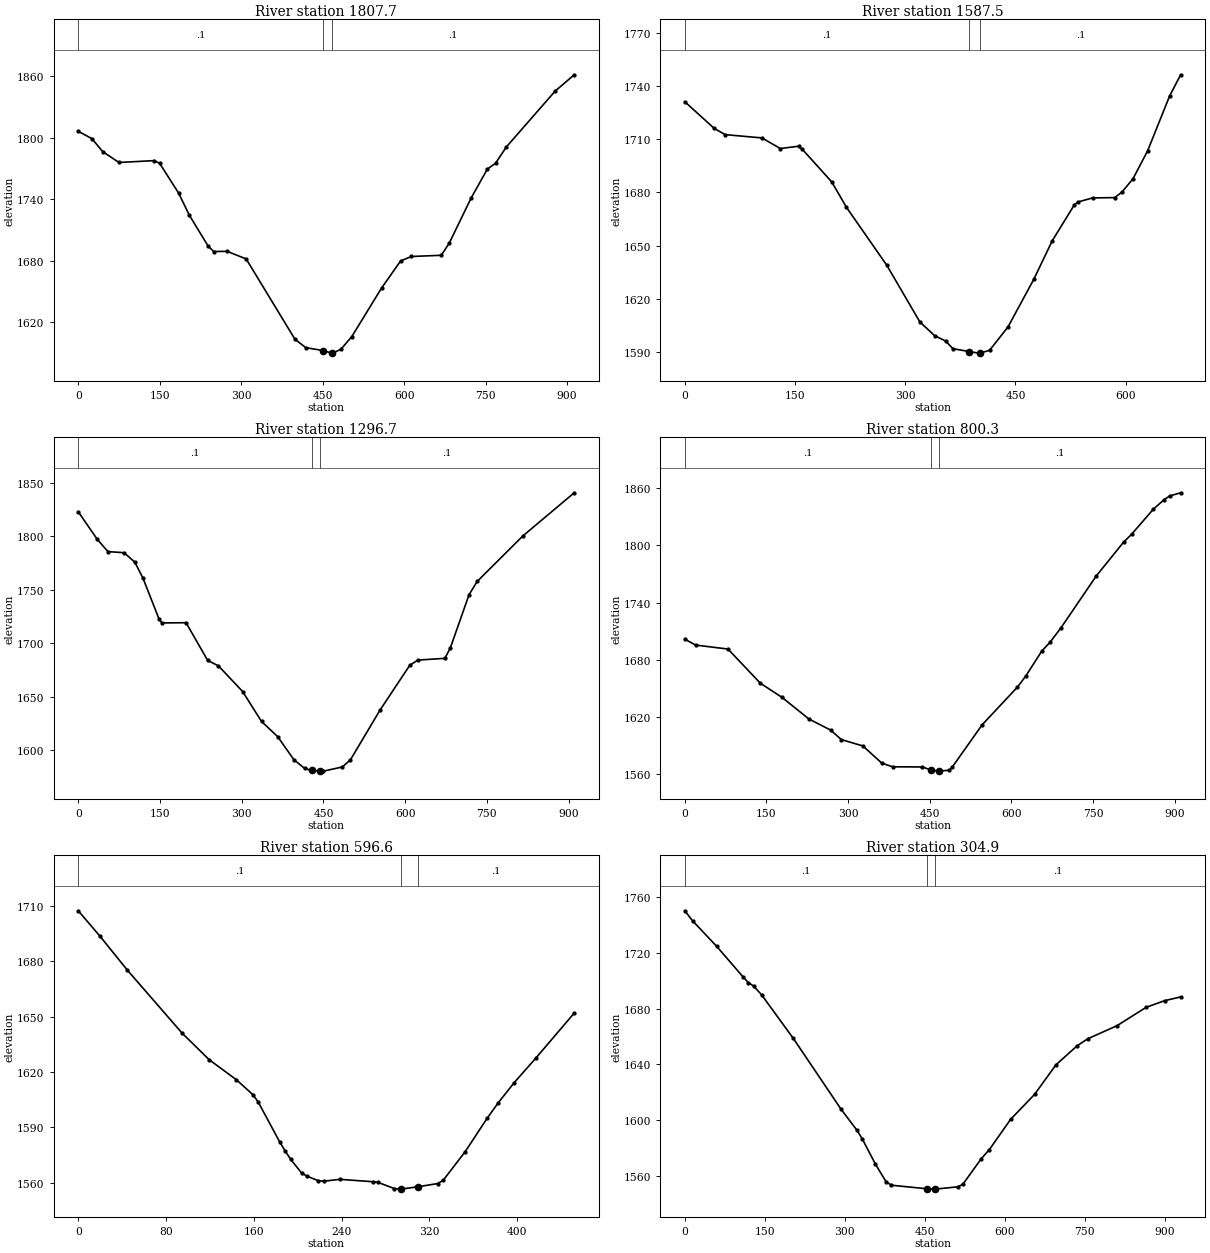
Type RM Length L Ch R = 1 ,1807.7,221.7,220.1,216.6
XS GIS Cut Line= 3
     1861859.160      224963.233     1861452.674      225175.679
     1861033.711      225351.488
#Sta/Elev= 30
       0 1806.31    24.9 1799.20    44.9 1786.53    74.8 1775.88   139.6 1777.71
   149.6 1775.15   184.5 1746.11   204.4 1724.35   239.3 1693.96   249.3 1688.89
   274.2 1689.03   309.1 1681.60   398.8 1603.21   418.8 1594.94   451.2 1592.03
   466.2 1589.61   468.6 1589.58   483.6 1593.40   503.6 1605.78   558.5 1653.28
   593.5 1679.71   613.4 1684.01   668.4 1685.19   683.3 1697.39   723.3 1741.18
   753.2 1769.46   768.2 1775.11   788.2 1791.09   878.1 1845.69   913.0 1861.54
#Mann= 3 , 0 , 0
       0     0.1       0   451.2   0.045       0   466.2     0.1       0
Bank Sta=   451.2,   466.2
Exp/Cntr=0.3,0.1

Type RM Length L Ch R = 1 ,1587.5,294.3,290.8,287.4
XS GIS Cut Line= 2
     1861712.173      224772.399     1861131.619      225116.431
#Sta/Elev= 30
       0 1731.28    40.0 1716.22    55.0 1712.68   105.0 1710.83   130.0 1704.82
   155.0 1706.14   160.0 1704.37   200.0 1685.96   220.0 1671.60   274.9 1638.85
   319.9 1606.82   339.9 1599.09   354.9 1596.03   364.9 1591.69   386.8 1590.09
   399.9 1589.18   401.8 1589.18   414.9 1590.80   439.9 1604.02   474.9 1630.86
   499.9 1652.55   529.9 1672.83   534.9 1674.59   554.9 1676.91   584.9 1677.09
   594.8 1680.14   609.8 1687.63   629.8 1703.45   659.8 1734.51   674.8 1746.49
#Mann= 3 , 0 , 0
       0     0.1       0   386.8   0.045       0   401.8     0.1       0
Bank Sta=   386.8,   401.8
Exp/Cntr=0.3,0.1

Type RM Length L Ch R = 1 ,1296.7,501.1,496.4,492.3
XS GIS Cut Line= 3
     1861574.544      224440.961     1861229.241      224737.319
     1860879.297      225028.591
#Sta/Elev= 30
       0 1823.06    34.6 1797.42    54.4 1785.85    84.1 1784.82   103.9 1775.84
   118.7 1760.98   148.4 1722.50   153.3 1719.13   197.8 1719.32   237.4 1684.08
   257.2 1678.97   301.7 1654.92   336.3 1626.97   366.0 1612.73   395.7 1591.22
   415.5 1582.98   428.4 1581.08   443.4 1580.59   450.1 1580.48   484.7 1584.38
   499.6 1591.07   554.0 1637.68   608.5 1679.49   623.3 1684.37   672.8 1685.99
   682.7 1695.36   717.3 1745.49   732.2 1757.91   816.3 1800.58   910.3 1840.84
#Mann= 3 , 0 , 0
       0     0.1       0   428.4   0.045       0   443.4     0.1       0
Bank Sta=   428.4,   443.4
Exp/Cntr=0.3,0.1

Type RM Length L Ch R = 1 ,800.3,204.9,203.7,201.4
XS GIS Cut Line= 3
     1861199.657      223985.773     1860924.549      224349.598
     1860637.563      224702.411
#Sta/Elev= 30
       0 1701.70    19.8 1695.54    79.3 1691.37   138.8 1655.54   178.5 1640.75
   228.1 1618.01   267.7 1606.48   287.6 1596.46   327.2 1589.78   361.9 1571.78
   381.8 1567.92   436.3 1567.79   452.4 1564.55   466.1 1563.40   467.4 1563.46
   486.1 1564.37   491.1 1567.42   546.1 1611.86   611.1 1651.48   626.0 1662.71
   656.0 1689.36   671.0 1698.48   691.0 1713.54   756.0 1768.03   806.0 1803.33
   821.0 1811.79   861.0 1838.12   880.9 1848.09   890.9 1851.89   910.9 1855.12
#Mann= 3 , 0 , 0
       0     0.1       0   452.4   0.045       0   467.4     0.1       0
Bank Sta=   452.4,   467.4
Exp/Cntr=0.3,0.1

Type RM Length L Ch R = 1 ,596.6,290,291.8,293.5
XS GIS Cut Line= 2
     1860919.132      223985.179     1860683.934      224371.211
#Sta/Elev= 30
       0 1707.42    19.9 1693.53    44.7 1675.23    94.4 1641.18   119.2 1626.67
   144.1 1615.76   159.0 1607.74   163.9 1603.75   183.8 1581.76   188.8 1576.89
   193.7 1572.49   203.7 1565.03   208.6 1563.39   218.6 1561.02   223.5 1560.70
   238.4 1561.72   268.2 1560.44   273.2 1560.05   288.1 1556.73   293.1 1556.41
   294.6 1556.46   309.6 1557.69   327.8 1559.45   332.8 1561.34   352.7 1576.78
   372.6 1594.79   382.5 1603.04   397.4 1614.24   417.3 1627.67   452.0 1651.90
#Mann= 3 , 0 , 0
       0     0.1       0   294.6   0.045       0   309.6     0.1       0
Bank Sta=   294.6,   309.6
Exp/Cntr=0.3,0.1

Type RM Length L Ch R = 1 ,304.9,109.3,105.2,101.2
XS GIS Cut Line= 3
     1860768.200      223747.878     1860462.797      224170.446
     1860369.485      224568.061
#Sta/Elev= 30
       0 1750.26    14.9 1742.96    59.6 1724.82   109.2 1702.82   119.2 1698.69
   129.1 1696.19   144.0 1689.94   203.6 1658.56   293.0 1607.77   322.8 1592.65
   332.7 1586.54   357.5 1568.29   377.4 1555.70   387.3 1553.18   454.8 1550.58
   466.8 1550.36   469.8 1550.38   511.4 1551.98   521.4 1553.81   556.2 1572.35
   571.2 1578.79   611.0 1600.49   655.9 1618.39   695.7 1639.52   735.6 1653.29
   755.5 1658.34   810.3 1667.70   865.0 1680.92   899.9 1685.74   929.8 1688.40
#Mann= 3 , 0 , 0
       0     0.1       0   454.8   0.045       0   469.8     0.1       0
Bank Sta=   454.8,   469.8
Exp/Cntr=0.3,0.1

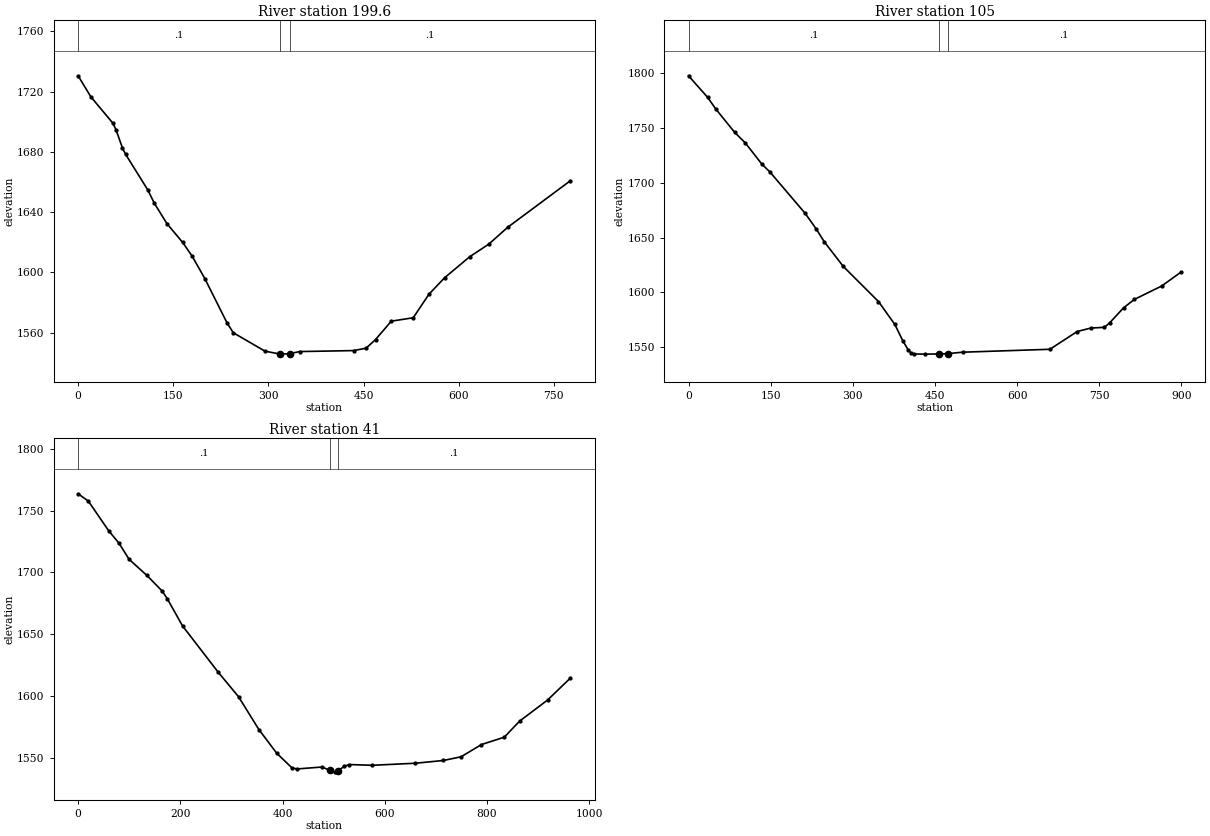
Type RM Length L Ch R = 1 ,199.6,96.1,94.6,93.1
XS GIS Cut Line= 3
     1860556.109      223770.433     1860377.154      224138.569
     1860349.033      224504.149
#Sta/Elev= 30
       0 1730.43    20.0 1716.51    54.9 1698.91    59.9 1694.40    69.9 1682.42
    74.9 1678.27   109.8 1654.67   119.8 1646.06   139.8 1632.38   164.7 1619.85
   179.7 1610.71   199.7 1595.81   234.6 1566.49   244.6 1559.85   294.5 1547.64
   318.4 1545.70   319.5 1545.67   333.4 1546.00   349.4 1547.37   434.1 1548.02
   453.9 1549.62   468.8 1555.34   493.6 1567.54   528.2 1569.82   553.0 1585.43
   577.8 1596.42   617.4 1610.38   647.2 1618.63   676.9 1629.79   776.0 1660.80
#Mann= 3 , 0 , 0
       0     0.1       0   318.4   0.045       0   333.4     0.1       0
Bank Sta=   318.4,   333.4
Exp/Cntr=0.3,0.1

Type RM Length L Ch R = 1 ,105,73.7,64,54.4
XS GIS Cut Line= 3
     1860504.979      223588.922     1860313.242      224061.874
     1860315.798      224450.462
#Sta/Elev= 30
       0 1797.66    34.7 1778.10    49.6 1767.50    84.2 1746.09   104.0 1736.22
   133.8 1717.14   148.6 1709.92   213.0 1672.12   232.9 1658.10   247.7 1646.32
   282.4 1623.80   346.8 1591.69   376.6 1570.86   391.4 1555.73   401.3 1547.45
   406.3 1544.66   411.2 1543.83   431.1 1543.68   458.2 1543.82   473.2 1544.12
   500.4 1545.44   659.8 1548.10   709.6 1564.29   734.5 1567.48   759.4 1568.11
   769.4 1572.45   794.3 1585.90   814.2 1593.64   864.1 1605.89   898.9 1618.41
#Mann= 3 , 0 , 0
       0     0.1       0   458.2   0.045       0   473.2     0.1       0
Bank Sta=   458.2,   473.2
Exp/Cntr=0.3,0.1

Type RM Length L Ch R = 1 ,41,41.8,41,40.1
XS GIS Cut Line= 4
     1860415.502      223535.235     1860264.692      223946.892
     1860268.895      224049.017     1860295.346      224470.915
#Sta/Elev= 30
       0 1763.69    19.9 1757.82    59.8 1733.74    79.7 1723.82    99.6 1710.71
   134.5 1697.60   164.4 1684.98   174.4 1678.77   204.3 1656.70   274.0 1619.28
   313.9 1599.36   353.7 1572.81   388.6 1553.62   418.5 1541.72   428.4 1540.88
   477.4 1542.44   492.9 1539.67   501.7 1538.30   507.9 1539.27   521.2 1543.09
   530.9 1544.43   575.4 1543.84   660.0 1545.50   714.7 1547.73   749.5 1550.74
   789.3 1560.64   834.0 1566.60   863.9 1579.59   918.6 1596.64   963.4 1614.50
#Mann= 3 , 0 , 0
       0     0.1       0   492.9   0.045       0   507.9     0.1       0
Bank Sta=   492.9,   507.9
Exp/Cntr=0.3,0.1